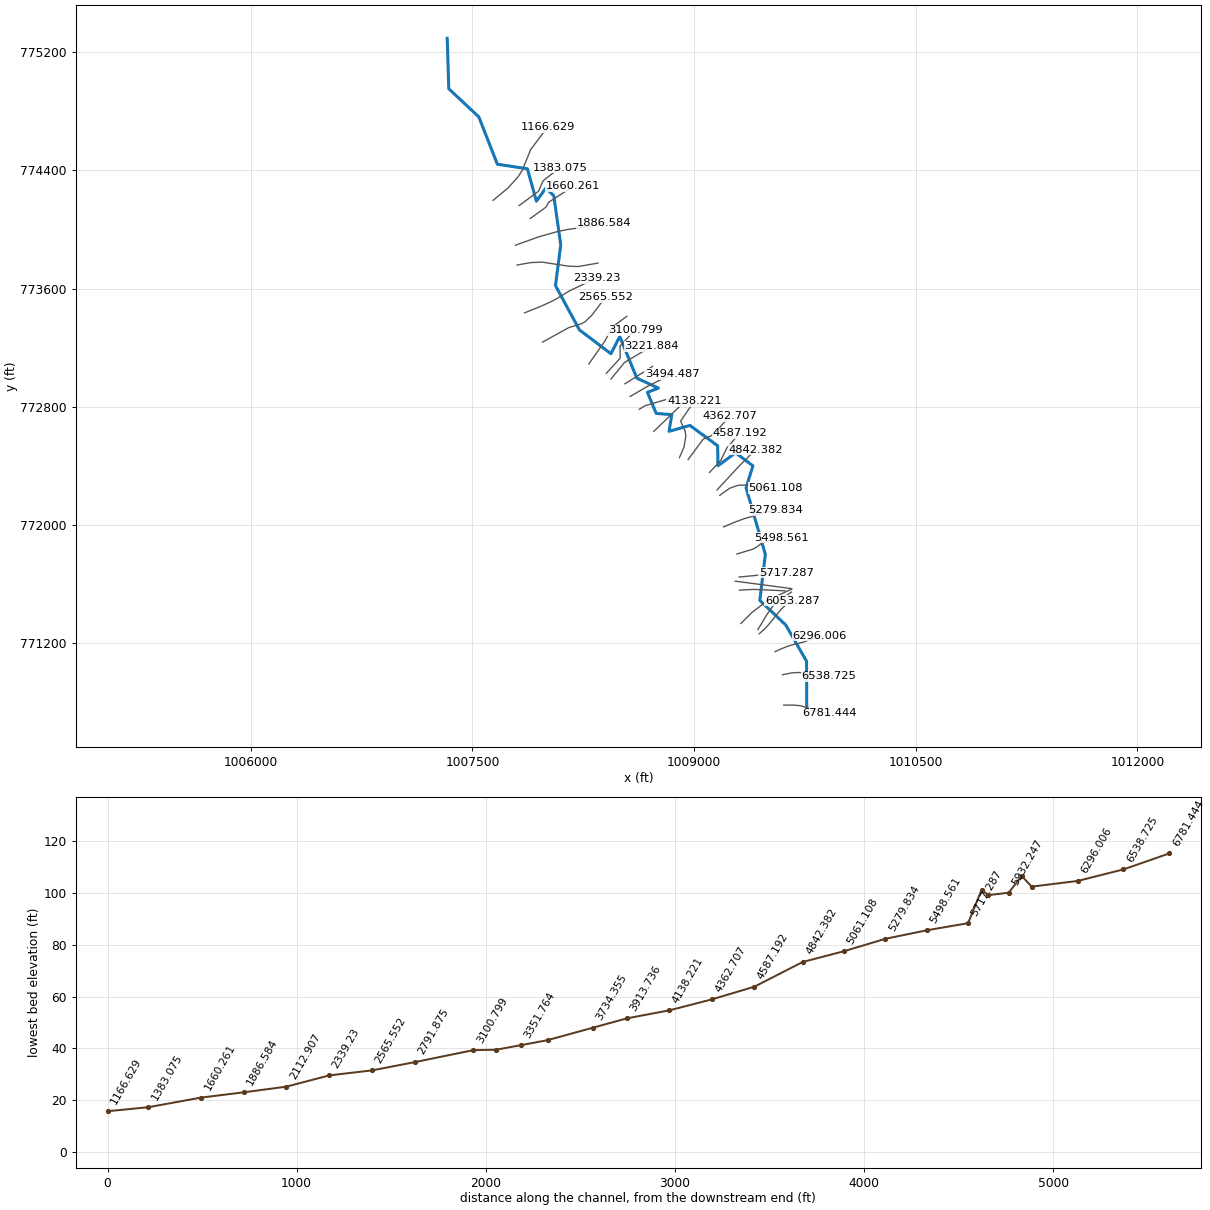
--- 199_ras.prj (project) ---

Proj Title=199
Current Plan=p01
Default Exp/Contr=0.3,0.1
English Units
Geom File=g01
Flow File=f01
Plan File=p01
Y Axis Title=Elevation
X Axis Title(PF)=Main Channel Distance
X Axis Title(XS)=Station
BEGIN DESCRIPTION:
RFD model 199 exported to HEC-RAS
END DESCRIPTION:

--- 199_ras.p01 (plan) ---

Plan Title=Plan 01
Program Version=4.10
Short Identifier=Plan 01
Geom File=g01
Flow File=f01
Subcritical Flow
Calc Critical at every XS
Secant Critical Depth

--- 199_ras.f01 (steady flow) ---

Flow Title=Flow 01
Program Version=5.01
Number of Profiles= 6
Profile Names=10yr,25yr,50yr,100yr,100plus,500yr
River Rch & RM=199,37,6781.444
  103.55   198.6  301.67  416.09  607.49 1364.43
River Rch & RM=199,37,5789.001
  103.93  199.34   302.8  417.65  609.77  1368.9
River Rch & RM=199,37,5498.561
  106.02  203.39  308.99  426.25  622.32 1393.39
River Rch & RM=199,37,5279.834
   124.6  239.45  364.23  502.89  734.22 1608.86
River Rch & RM=199,37,5061.108
  134.21  258.09  392.81  542.55  792.12 1718.53
River Rch & RM=199,37,4842.382
  139.28     268  408.05  563.79  823.14 1777.38
River Rch & RM=199,37,4587.192
  140.69  270.75  412.28  569.66  831.71 1793.48
River Rch & RM=199,37,4362.707
  141.05  271.44  413.34  571.13  833.85  1797.5
River Rch & RM=199,37,4138.221
  146.72  282.54  430.44  594.99  868.69 1863.26
River Rch & RM=199,37,3913.736
  154.67  298.05  454.28  628.15   917.1 1953.45
River Rch & RM=199,37,3734.355
  178.17  343.81  524.56  725.85 1059.74 2214.84
River Rch & RM=199,37,3494.487
  179.64  346.69  529.01  732.06 1068.81 2231.46
River Rch & RM=199,37,3221.884
  180.46  348.29  531.48  735.51 1073.84 2240.67
River Rch & RM=199,37,3100.799
  181.27  349.89  533.94  738.95 1078.87 2249.87
River Rch & RM=199,37,2791.875
  188.56  364.19  556.02  769.78 1123.88 2331.98
River Rch & RM=199,37,2565.552
  191.14  369.25  563.82  780.68 1139.79  2360.9
River Rch & RM=199,37, 2339.23
  191.94  370.82  566.26  784.08 1144.75 2369.91
River Rch & RM=199,37,2112.907
   196.9  380.56   581.3  805.08 1175.42 2425.48
River Rch & RM=199,37,1886.584
  222.86  431.55  660.06  915.11 1336.06 2713.34
River Rch & RM=199,37,1660.261
   226.2  438.14  670.29  929.44 1356.98  2750.8
River Rch & RM=199,37,1166.629
  227.25  440.22  673.52  933.97  1363.6 2762.68
River Rch & RM=199,37,950.1835
  229.65  444.97  680.89  944.33 1378.72 2789.75
River Rch & RM=199,37,733.7377
  232.93  451.47     691  958.52 1399.43 2826.81
River Rch & RM=199,37,517.2919
  235.31  456.19  698.33  968.81 1414.46 2853.64
River Rch & RM=199,37, 300.846
   243.5   472.4  723.49  1004.1 1465.99 2945.14
River Rch & RM=199,37, 84.4002
  244.97  475.32  728.03 1010.48  1475.3 2961.65
River Rch & RM=199,37, 27.2012
  245.12  475.61  728.48 1011.12 1476.23  2963.3
Boundary for River Rch & Prof#=199,37,1
Up Type= 0
Dn Type= 2
Boundary for River Rch & Prof#=199,37,2
Up Type= 0
Dn Type= 2
Boundary for River Rch & Prof#=199,37,2
Up Type= 0
Dn Type= 2
Boundary for River Rch & Prof#=199,37,2
Up Type= 0
Dn Type= 2
Boundary for River Rch & Prof#=199,37,2
Up Type= 0
Dn Type= 2
Boundary for River Rch & Prof#=199,37,2
Up Type= 0
Dn Type= 2

--- 199_ras.g01 (geometry) ---

Geom Title=199
Program Version=4.10

River Reach=199,37
Reach XY= 30
1009762.70172371770760.5731723661009761.07486596771078.085336468
1009620.79708818771322.5297809221009444.92903262771489.543669812
1009482.40168789771800.8065401321009351.81570695772251.370333881
1009398.05403264772400.1339475971009280.86653261772488.675614273
1009161.94292152772401.0020031681009159.33875484772536.418669817
1008971.83875483772673.5714475791008830.34569928772633.640892055
1008849.44292146772746.488114265 1008743.5401437772755.168669808
1008684.51236592772897.5297809421008759.16514372772926.175614247
1008612.72370261772993.5905979211008497.01236592773275.133947573
1008437.20322258773158.9990805851008224.31838209773319.712690552
1008062.11653261773619.7520031451008097.57059839773895.790157771
 1008050.8318104774227.3908920331007997.01236593774280.342280919
1007932.85113004774191.1451338091007872.01236592774410.550614253
1007668.88310936 774441.353288291007543.18242927774761.676180478
1007340.05882292774952.1127700171007329.47764372775293.363114275

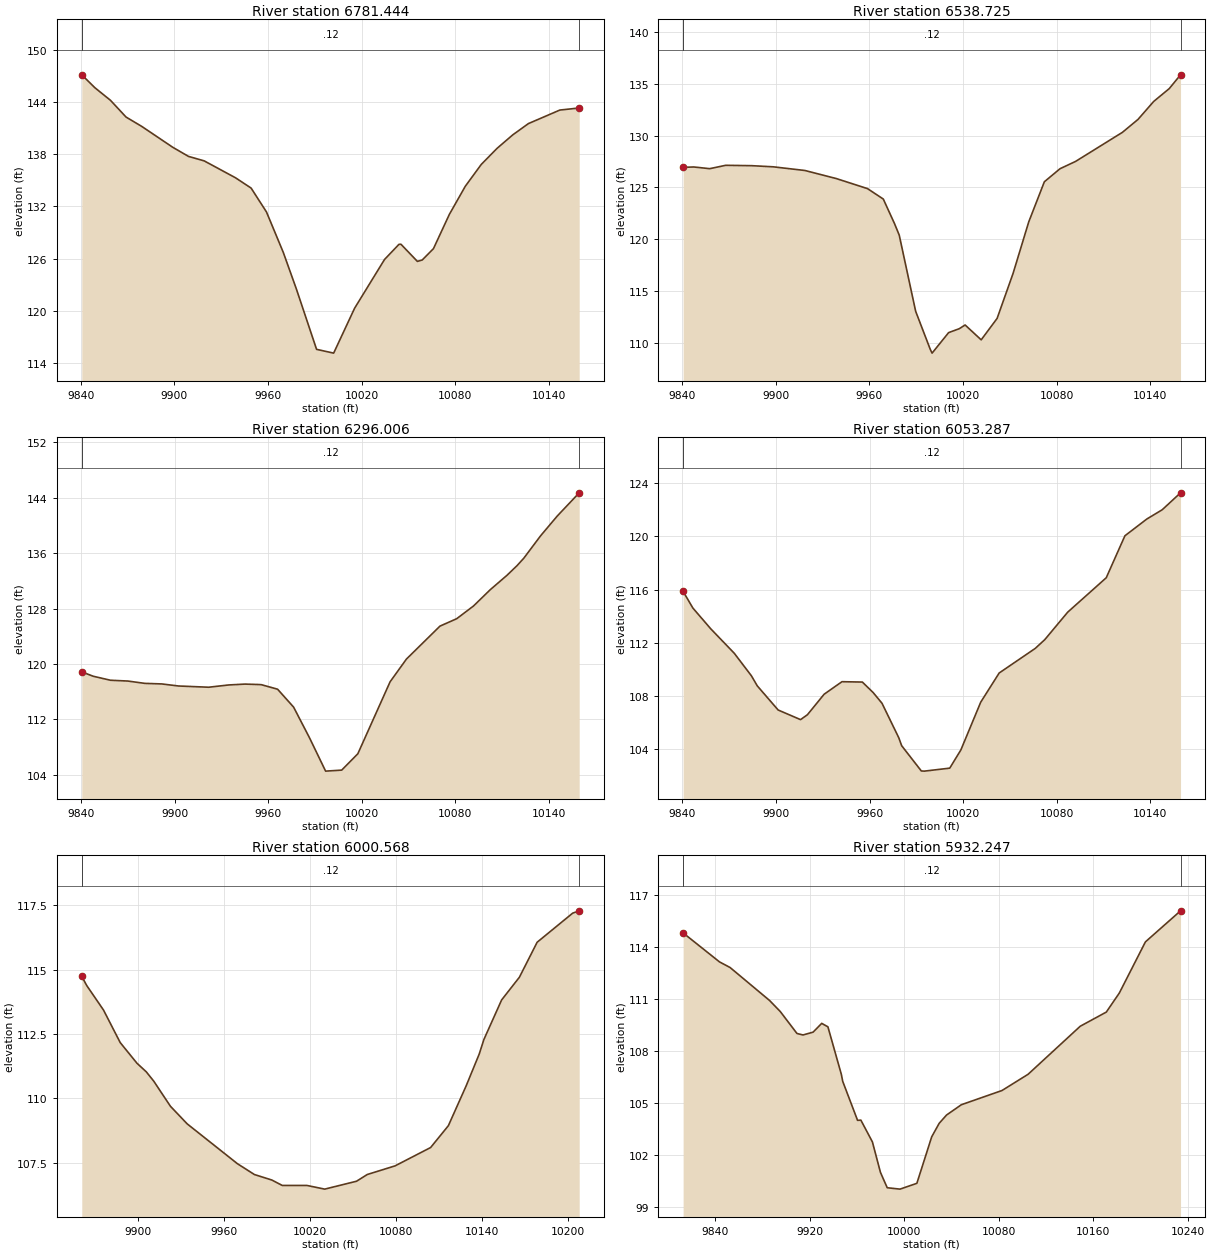
Type RM Length L Ch R = 1 ,6781.444,242.719200,242.719200,242.719200
XS GIS Cut Line= 6
1009606.61346362770780.5595819781009669.56705792770781.256470593
1009715.88084511770777.2387869691009743.18724671770770.190348906
 1009817.9115275770740.3433533451009917.32490021770724.942891428
#Sta/Elev= 30
9840.568147.12619848.955145.64679858.955144.19859868.956142.27329878.957 141.207
9898.958138.79489908.979137.75539919.016137.24349939.091135.30179949.129134.1151
 9958.97131.37379969.759126.72549978.214122.48849991.092  115.5910002.05115.1551
10015.48120.313410034.66125.912310043.91 127.65110045.19127.664310055.72125.6953
10058.79125.848810066.02127.153510076.24131.098810086.45134.324410096.66 136.827
10106.78138.675110116.85140.225810126.92141.524510147.06143.078810159.47143.3166
#Mann= 3 , 0 , 0
9840.568    0.12       09840.568    0.12       010159.47    0.12       0
#XS Ineff= 2 , 0
       0                               0
Bank Sta=9840.568,10159.47
Exp/Cntr=0.3,0.1

Type RM Length L Ch R = 1 ,6538.725,242.719100,242.719100,242.719100
XS GIS Cut Line= 6
1009598.27509919770986.3340337651009659.99619225770998.748704279
1009706.32737706771002.0274289441009732.17196713770998.264324506
1009806.54227896770976.9237375851009912.23343101  770975.4313369
#Sta/Elev= 30
9840.557126.95029847.417126.98299857.617126.81939867.817127.14439884.504 127.109
9898.418126.99719918.625126.64379938.688125.86619958.782124.88959968.887123.8814
9976.135121.48939979.111120.39269989.635113.0307    9999109.351210000.17108.9838
10010.76110.965710017.62111.346710021.35111.705810031.65110.268410041.86112.3408
10052.07116.681410062.13121.670910072.15125.552510082.17126.812210092.19127.5225
10122.22130.334410132.22131.585510142.22133.315110152.22134.560710159.46135.8933
#Mann= 3 , 0 , 0
9840.557    0.12       09840.557    0.12       010159.46    0.12       0
#XS Ineff= 2 , 0
       0                10031.09       0
Bank Sta=9840.557,10159.46
Exp/Cntr=0.3,0.1

Type RM Length L Ch R = 1 ,6296.006,242.719200,242.719200,242.719200
XS GIS Cut Line= 6
1009548.32382506771142.5741145321009587.23708197771160.639036146
1009627.90059964771176.9776404651009661.20550275771187.555723889
  1009741.707166771207.7518307611009848.09072013771249.599988472
#Sta/Elev= 30
9840.495118.85589847.855118.2266 9858.88117.65089870.005117.5346 9880.93117.1985
9891.763117.1178 9902.54116.81959921.916116.64249934.669 116.9699945.161117.0945
9953.722117.03259955.653117.0092 9966.06116.35659976.326113.77739986.593109.3195
9996.859104.536410007.18104.682210017.53107.041910038.23117.430510048.71120.7075
 10070.2125.458810080.95126.531510091.69128.360610102.44130.711810113.18132.7927
10119.61134.182610123.93135.249110134.68138.476810145.42141.343210159.49 144.692
#Mann= 3 , 0 , 0
9840.495    0.12       09840.495    0.12       010159.49    0.12       0
#XS Ineff= 2 , 0
       09928.835                       0
Bank Sta=9840.495,10159.49
Exp/Cntr=0.3,0.1

Type RM Length L Ch R = 1 ,6053.287,52.719000,52.719000,52.719000
XS GIS Cut Line= 6
1009440.34066631771263.2084036441009473.06667352771292.282447598
1009498.06922013771318.0759410011009590.39877102771431.175318564
1009620.20203751771457.5802830831009664.82424526771486.856350459
#Sta/Elev= 30
9840.493  115.879846.726114.62219858.247 113.0539873.304111.21589884.269109.5248
9888.053108.76529901.414106.95159915.782106.22749920.191106.59579930.923108.1399
9942.358109.08069955.417109.05269962.346 108.2639968.022107.45769978.773104.8648
9980.626104.2668 9993.23102.36649995.201102.354510011.46102.5793 10018.6103.9523
10031.32107.541510043.15109.734110066.26111.5821 10072.4 112.244 10087.1114.3109
10111.81116.897610123.77120.053410137.83121.314310147.69122.011510159.44123.2843
#Mann= 3 , 0 , 0
9840.493    0.12       09840.493    0.12       010159.44    0.12       0
#XS Ineff= 2 , 0
       09953.787                       0
Bank Sta=9840.493,10159.44
Exp/Cntr=0.3,0.1

Type RM Length L Ch R = 1 ,6000.568,68.321200,68.321200,68.321200
XS GIS Cut Line= 4
1009431.90075788771292.0344634951009493.74971619771395.116060719
1009539.32263288771459.1351579281009658.68027177771545.940713495
#Sta/Elev= 28
9861.166114.73259864.624114.37749876.286113.42799887.948112.1629 9899.61111.3618
9906.063111.02999911.272110.66799922.934109.69019934.595109.00829969.581 107.462
9981.378107.04289993.511106.829810000.78 106.61910018.02106.618510030.34106.4764
10052.51 106.78310059.96107.043810079.35107.379510104.08108.090610116.44108.9379
10128.81110.481710137.94 111.72110141.17112.282710153.54113.8208 10165.9114.7004
10178.27116.0595   10203117.187910207.55117.2784
#Mann= 3 , 0 , 0
9861.166    0.12       09861.166    0.12       010207.55    0.12       0
#XS Ineff= 2 , 0
       0 9963.83                       0
Bank Sta=9861.166,10207.55
Exp/Cntr=0.3,0.1

Type RM Length L Ch R = 1 ,5932.247,108.228700,108.228700,108.228700
XS GIS Cut Line= 4
1009316.88339677771333.267102361 1009391.7531884771408.136894032
1009503.51534122771492.7723107041009661.93548009771566.557032943
#Sta/Elev= 30
9812.961 114.8339843.696113.15959852.724 112.8319886.122110.9242 9895.15110.2865
9909.292109.01649914.407108.93179922.916109.09389930.211109.60179935.459109.4018
9946.775106.66589948.003106.24489960.547103.9922 9963.34 104.0059973.091 102.748
9979.904100.98489985.635 100.0959996.468100.014710010.72 100.35110023.27103.0399
 10029.6103.821210035.81104.298710048.35104.896210082.74105.7182 10104.8106.6557
10148.92 109.43510170.99110.254510182.02111.357710204.08114.3148 10233.8116.1111
#Mann= 3 , 0 , 0
9812.961    0.12       09812.961    0.12       0 10233.8    0.12       0
#XS Ineff= 2 , 0
       09962.755                       0
Bank Sta=9812.961,10233.8
Exp/Cntr=0.3,0.1

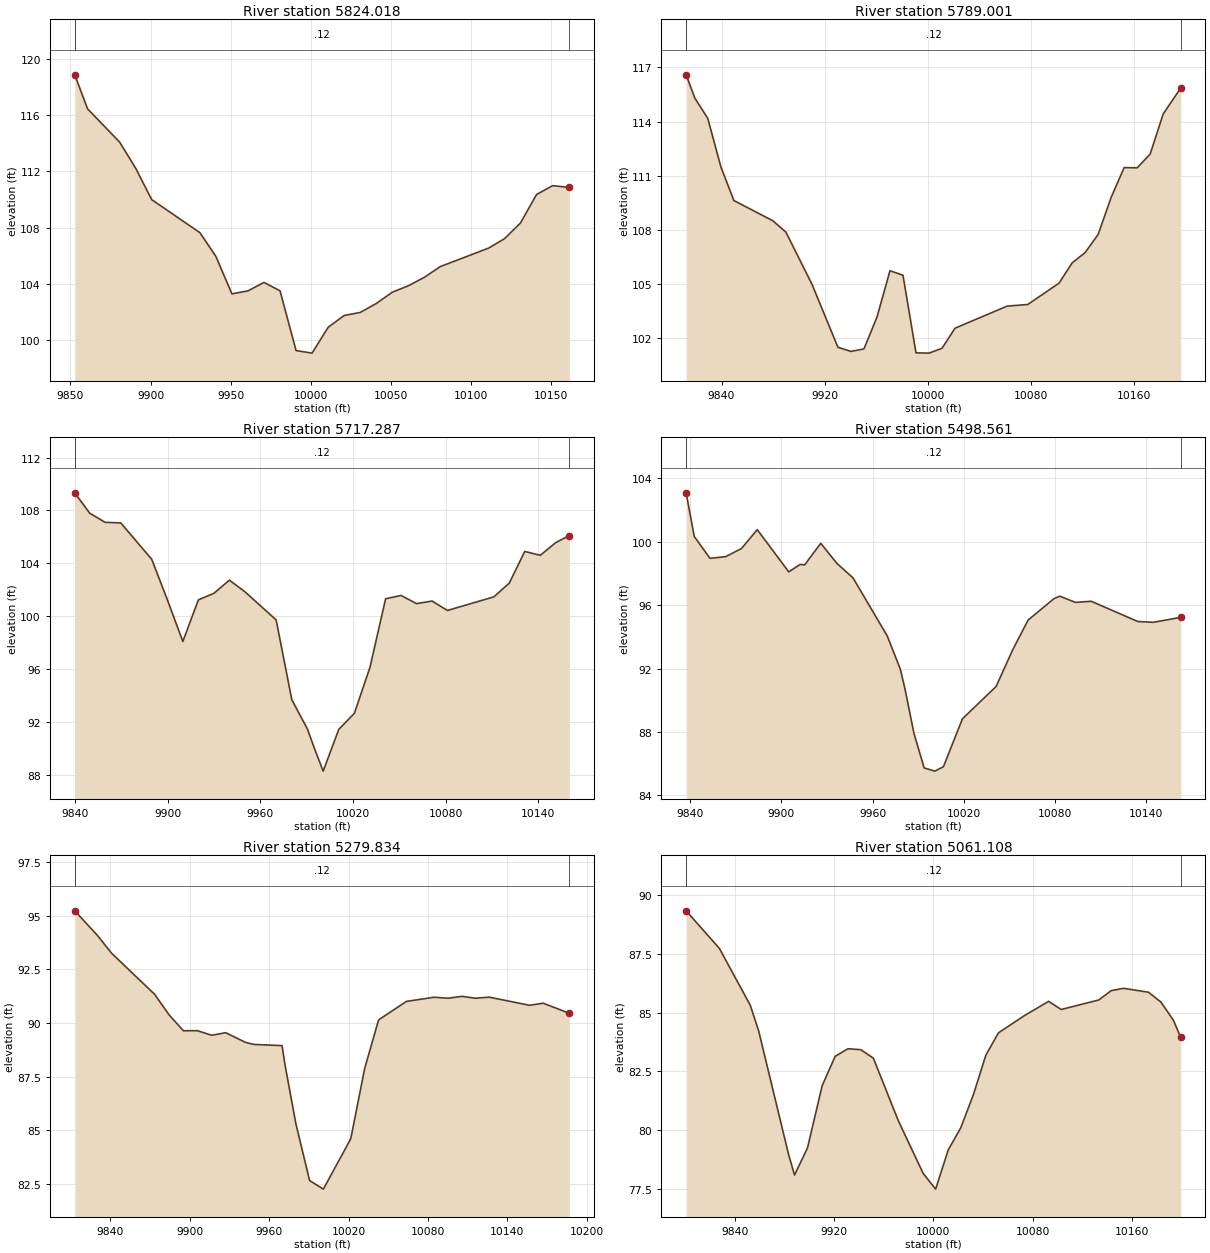
Type RM Length L Ch R = 1 ,5824.018,35.017200,35.017200,35.017200
XS GIS Cut Line= 3
1009307.02778402771558.9993677441009399.70732129771563.964342952
1009615.40791097771554.586056441
#Sta/Elev= 27
9852.671118.87269860.654116.45479880.683114.08689890.697112.22729900.712109.9938
9930.755107.64619940.769105.95919950.781  103.29 9960.79 103.504  9970.8104.1018
9980.809103.50949990.81999.2557610000.8399.0738510010.84100.908510020.85101.7519
10030.86101.967410040.87102.602610050.88103.406310060.88103.862210070.89104.4663
 10080.9105.233510110.93106.540210120.94107.214110130.95108.338410140.96110.3613
10150.97110.987510161.39110.8637
#Mann= 3 , 0 , 0
9852.671    0.12       09852.671    0.12       010161.39    0.12       0
#XS Ineff= 2 , 0
       09969.675                       0
Bank Sta=9852.671,10161.39
Exp/Cntr=0.3,0.1

Type RM Length L Ch R = 1 ,5789.001,71.713900,71.713900,71.713900
XS GIS Cut Line= 2
1009278.34126058771619.6823980961009658.43769616771569.480982095
#Sta/Elev= 30
9812.561116.58869819.278115.30499829.364114.17139839.451111.50249849.538109.6329
9879.799108.50839889.885107.88269910.059105.00329930.233101.5072 9940.32101.2785
9950.407101.41679960.493103.1745 9970.58105.74439980.667105.49519990.754101.1988
10000.84 101.18310010.93101.450710021.01102.563410061.36103.784110077.44103.8754
10101.71105.0603 10111.8106.176210121.88106.750210131.97107.751610142.06109.8059
10152.14111.453410162.23111.439810172.32112.2046 10182.4 114.42310195.96115.8539
#Mann= 3 , 0 , 0
9812.561    0.12       09812.561    0.12       010195.96    0.12       0
#XS Ineff= 2 , 0
       09971.452                       0
Bank Sta=9812.561,10195.96
Exp/Cntr=0.3,0.1

Type RM Length L Ch R = 1 ,5717.287,218.726300,218.726300,218.726300
XS GIS Cut Line= 6
1009305.38662759771647.6640553121009423.33183161771658.994891795
 1009463.2909011771665.698384549 1009465.2676445771666.002498918
1009505.27533656771671.722901836 1009623.7852832 771675.83158216
#Sta/Elev= 30
9839.994 109.3339849.652107.79239859.698107.09779869.744107.05989889.836104.2969
9899.882101.24899909.928 98.08689919.974101.2299 9930.02101.73019940.066102.7259
9950.112101.84959970.31499.714899980.45493.674179990.59391.455549994.77990.08988
10000.73 88.276610010.8391.4347310020.9392.6497310031.03 96.133910041.14101.3179
10051.15101.568410061.15100.951210071.16101.146910081.16100.433210111.18101.4612
10121.19102.507910131.19104.8999 10141.2104.603310151.21105.5636   10160106.0996
#Mann= 3 , 0 , 0
9839.994    0.12       09839.994    0.12       0   10160    0.12       0
#XS Ineff= 2 , 0
       09955.345                       0
Bank Sta=9839.994,10160
Exp/Cntr=0.3,0.1

Type RM Length L Ch R = 1 ,5498.561,218.726200,218.726200,218.726200
XS GIS Cut Line= 6
1009289.86519302771803.7614175791009397.81049148771836.179290258
1009422.59706057771849.5590180511009455.64721208771874.853967153
1009478.76347393771885.6774725481009592.70485271771913.072270537
#Sta/Elev= 30
9837.301103.08229842.623100.33119852.98798.950979863.35199.059139873.71599.56998
9884.079100.75939904.80698.098949912.326 98.56979915.24198.53473 9925.8699.90032
 9936.4898.63155  9947.197.717579969.61994.055239978.25291.951549981.28390.71334
9987.17687.91647  9993.9  85.732   1000185.5315210006.5885.8136610019.0788.82987
10041.2590.8728110051.8993.1293410062.2995.0583910079.2696.40598 10083.196.56499
 10093.5 96.172310103.7696.2446710134.3994.96891 10144.694.9163610162.6795.22761
#Mann= 3 , 0 , 0
9837.301    0.12       09837.301    0.12       010162.67    0.12       0
#XS Ineff= 2 , 0
       0                10092.76       0
Bank Sta=9837.301,10162.67
Exp/Cntr=0.3,0.1

Type RM Length L Ch R = 1 ,5279.834,218.726300,218.726300,218.726300
XS GIS Cut Line= 6
1009199.38965161 771986.81114848 1009275.1643766772018.885592609
1009344.23906222772044.2162035451009393.28949171772057.813566447
 1009476.0725295772084.3587486771009554.32086116772100.965106661
#Sta/Elev= 29
9813.14495.229089830.09594.095379840.95493.252179873.53191.33226 9884.3990.37739
9895.24989.634659905.90489.637399916.55589.423469927.20689.544059942.23289.09039
9948.50988.996279969.79288.941489971.85988.09871 9980.1985.305399990.58982.64806
10000.9882.24641 10021.784.59405 10032.287.87278 10042.790.1356910043.4490.16939
10063.71 91.002310084.7191.1988710095.2191.1517310105.7191.2391310115.9691.15082
10126.1991.2023610156.8690.8225210167.0890.9200110186.8390.44993
#Mann= 3 , 0 , 0
9813.144    0.12       09813.144    0.12       010186.83    0.12       0
#XS Ineff= 2 , 0
       09952.968        10096.02       0
Bank Sta=9813.144,10186.83
Exp/Cntr=0.3,0.1

Type RM Length L Ch R = 1 ,5061.108,218.726300,218.726300,218.726300
XS GIS Cut Line= 6
1009173.68089883772200.3883064171009240.71306065772248.368715825
1009298.40250941772269.0034131721009349.16864928772270.298548463
1009471.39597251772252.2553194591009550.91262157772250.322759977
#Sta/Elev= 30
9801.01589.339829827.81287.734789852.619 85.31469859.33784.231089883.49278.94788
9888.258 78.08039898.66779.231369910.49481.887019920.93583.138169931.25283.46042
9941.56983.421869951.69483.058739971.73880.399779991.74178.1530610001.8177.47838
10011.9279.1456610022.0280.0904710032.1381.4915210042.2483.1875710052.3584.13786
10072.5784.8504110092.7885.4826710102.8985.1340310133.0985.5402510143.1185.93797
10153.12 86.037310173.1385.8707410183.1485.4509810193.1484.6824110199.0583.94573
#Mann= 3 , 0 , 0
9801.015    0.12       09801.015    0.12       010199.05    0.12       0
#XS Ineff= 2 , 0
       09945.801        10068.94       0
Bank Sta=9801.015,10199.05
Exp/Cntr=0.3,0.1

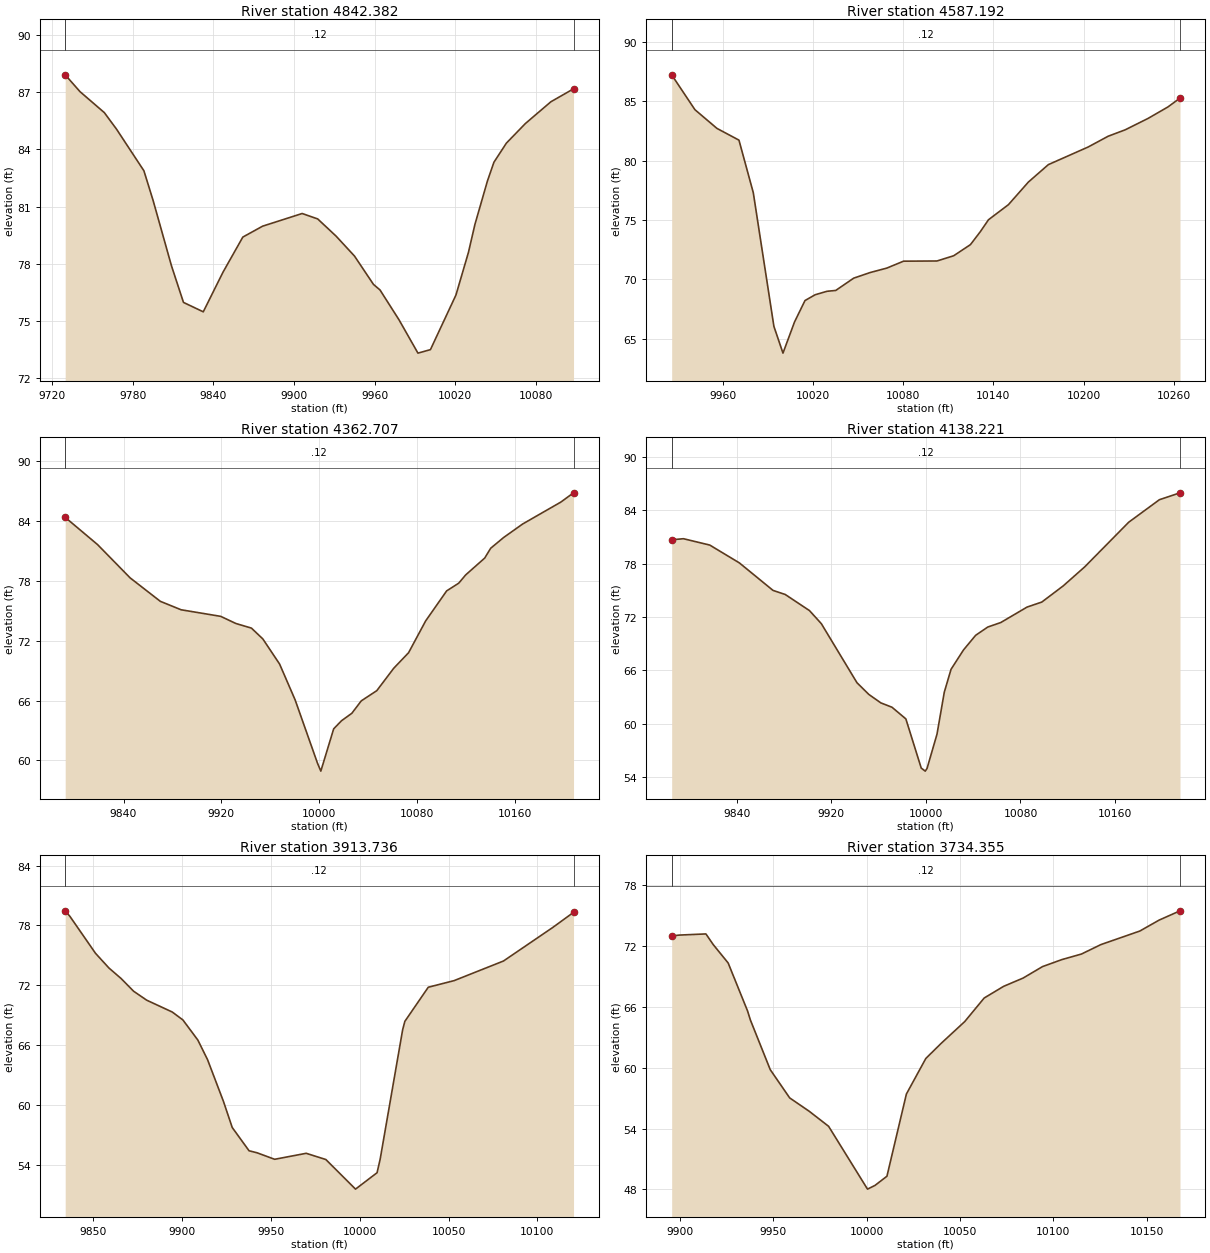
Type RM Length L Ch R = 1 ,4842.382,255.190200,255.190200,255.190200
XS GIS Cut Line= 3
1009155.20804954772236.9129357191009298.43721622772391.860852346
1009416.92679957772510.350435719
#Sta/Elev= 30
9729.62287.901699740.63487.020849758.77985.91993 9767.8785.051819788.24382.87295
9795.106 81.31399808.72477.904049817.70775.975469832.43975.482649847.17177.56298
9861.90379.398199876.63579.97054  9906.180.634499917.66680.350259931.28479.45452
9945.06778.405329959.20976.919079964.05176.630069978.19375.068119992.33573.31793
10001.6473.5012610020.6276.3613810029.9278.5919710034.7680.0623210044.0682.33401
 10048.983.31928 10058.284.3231610072.3585.3493510091.3386.48969 10108.287.16749
#Mann= 3 , 0 , 0
9729.622    0.12       09729.622    0.12       0 10108.2    0.12       0
#XS Ineff= 2 , 0
       09922.779                       0
Bank Sta=9729.622,10108.2
Exp/Cntr=0.3,0.1

Type RM Length L Ch R = 1 ,4587.192,224.485100,224.485100,224.485100
XS GIS Cut Line= 4
1009104.42679954772355.4025190321009181.24971619772437.433769047
1009221.61429957772520.7671023611009308.85388285772621.027519032
#Sta/Elev= 30
9926.18787.234669941.65584.297199956.28482.722629970.91381.733939980.43777.30901
9994.13866.0496110000.1763.7949610007.84 66.4166 10014.868.2222210021.5468.71093
10029.4369.0031810035.2469.0745710047.1870.1087810058.0970.58155 10069.270.95676
10080.3171.5394810102.5471.5552410113.6571.9967910124.7672.9313810131.1773.99325
10136.7875.0292310150.0376.2987110163.2978.2020210176.5579.6699910203.0681.15764
10216.3182.0614110227.7382.6079510242.8283.5613510256.0884.5307310264.0785.27624
#Mann= 3 , 0 , 0
9926.187    0.12       09926.187    0.12       010264.07    0.12       0
#XS Ineff= 2 , 0
       0                               0
Bank Sta=9926.187,10264.07
Exp/Cntr=0.3,0.1

Type RM Length L Ch R = 1 ,4362.707,224.485200,224.485200,224.485200
XS GIS Cut Line= 6
1008959.52038159772442.0115287081009058.00229233 772575.98520362
1009074.92779197772589.2762870531009111.10194136772600.767924399
1009137.89478068772619.0626585791009241.68096251772736.843435792
#Sta/Elev= 30
9792.342 84.38369818.76681.654489845.38578.314869870.06375.961889887.04875.11368
9919.41874.453659931.75773.740049944.52273.274379953.87372.184779967.54669.66849
9980.245 66.07039998.494 59.727610001.2358.9268410011.7363.1683710018.1463.98238
10026.5764.7288110034.27 65.974210046.9867.0010710060.8469.2502410072.9270.80177
10086.8973.9941310104.0577.0071710113.93 77.7835 10119.678.6100710135.1580.30024
10140.0481.28602 10150.782.3709410166.1683.7179810197.3585.9152110207.7486.84594
#Mann= 3 , 0 , 0
9792.342    0.12       09792.342    0.12       010207.74    0.12       0
#XS Ineff= 2 , 0
       0                               0
Bank Sta=9792.342,10207.74
Exp/Cntr=0.3,0.1

Type RM Length L Ch R = 1 ,4138.221,224.485100,224.485100,224.485100
XS GIS Cut Line= 6
1008900.96608573772456.0703891321008931.61778477772526.101222384
1008944.12481064772600.0504171461008940.36054198772634.260160705
1008908.85127742772702.7031627291009001.51032467772838.453309518
#Sta/Elev= 30
9785.11180.668839795.053 80.78569817.32180.072859842.33878.072429870.796 74.9846
9881.06474.52922  9901.672.720759911.65471.247439941.77264.621539951.77563.31152
9961.92462.362269971.37861.871049983.09660.561919996.08655.043419999.48254.70103
   1000155.0014510009.4158.84407 10015.663.5692810021.2966.12944 10031.9 68.3155
10042.1169.9468210052.3870.8758910063.3171.3766310085.5873.1149610098.0273.67547
10116.1575.4940910134.2577.6209110171.5282.6395110197.4385.1628710214.8585.93655
#Mann= 3 , 0 , 0
9785.111    0.12       09785.111    0.12       010214.85    0.12       0
#XS Ineff= 2 , 0
       0                               0
Bank Sta=9785.111,10214.85
Exp/Cntr=0.3,0.1

Type RM Length L Ch R = 1 ,3913.736,179.381600,179.381600,179.381600
XS GIS Cut Line= 2
1008727.25666067772633.1802968231008933.41985509772831.748005137
#Sta/Elev= 28
9834.08479.465089836.70778.918679851.12375.221259858.719 73.74269865.53872.69575
9872.60371.420459879.95370.526579894.36869.339059900.37168.544699908.78366.53305
9914.25664.567459923.19860.39428 9928.1457.785019937.61355.457089942.02455.26085
9952.029 54.60499969.79255.203469980.85954.58084 9997.5651.6194110009.6953.26141
10011.4454.62016 10024.167.5683210025.3368.4040710038.5271.81911 10053.172.48217
10080.8674.4422710108.6377.8006310120.3279.31112
#Mann= 3 , 0 , 0
9834.084    0.12       09834.084    0.12       010120.32    0.12       0
#XS Ineff= 2 , 0
       0                               0
Bank Sta=9834.084,10120.32
Exp/Cntr=0.3,0.1

Type RM Length L Ch R = 1 ,3734.355,239.868000,239.868000,239.868000
XS GIS Cut Line= 3
1008629.60041067772782.9198801371008666.49277177772806.791407943
1008885.67679954772870.810505137
#Sta/Elev= 28
9895.62272.953259899.45173.057049913.96473.172769917.85972.127129925.87570.31161
9936.26665.586129937.786 64.69459948.427 59.80059958.84457.016129969.26255.70615
 9979.6854.2201310000.5248.0301510004.5148.3934510010.9349.2987310021.3557.39788
10031.7760.9055710040.18 62.4262 10052.664.5361410063.0266.8574910073.4468.00868
10083.8668.8229210094.2869.9544210104.6970.6473710115.1171.1895310125.5372.12154
10146.3773.4558710156.7874.5392910167.9175.44847
#Mann= 3 , 0 , 0
9895.622    0.12       09895.622    0.12       010167.91    0.12       0
#XS Ineff= 2 , 0
       0                               0
Bank Sta=9895.622,10167.91
Exp/Cntr=0.3,0.1

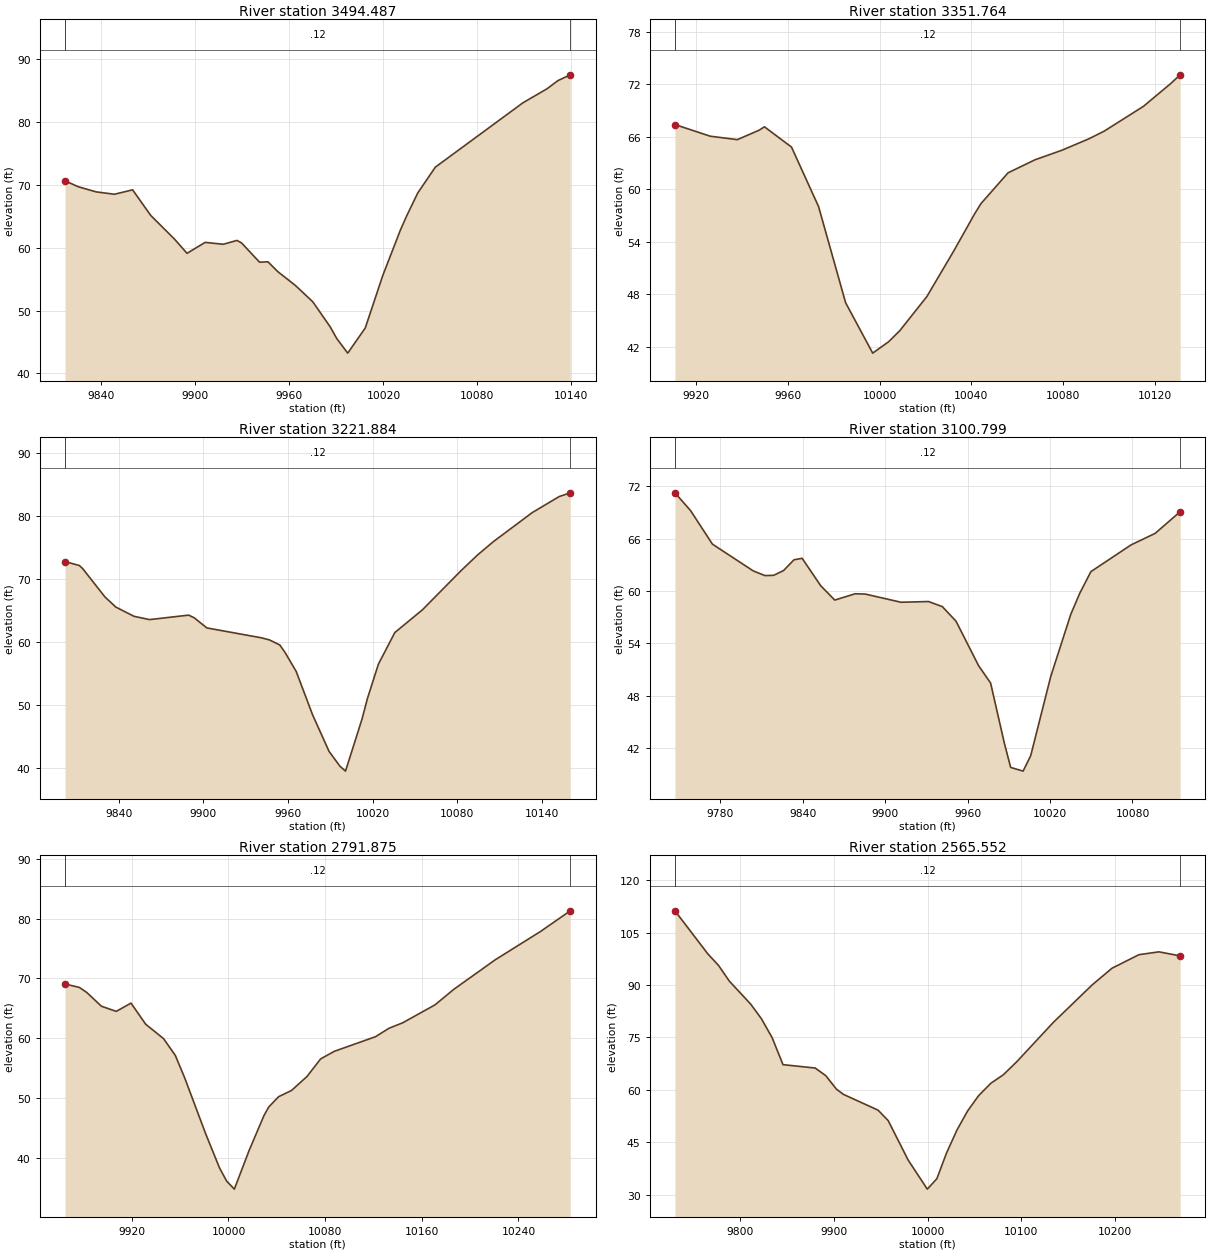
Type RM Length L Ch R = 1 ,3494.487,142.723200,142.723200,142.723200
XS GIS Cut Line= 3
 1008567.7514523772869.7254357041008684.93895233772938.084810704
1008852.03964674773021.635157943
#Sta/Elev= 30
 9816.7570.634379825.14169.696269836.71868.870579848.29568.497979859.87269.20067
9871.44965.130519886.75761.324319894.60359.10062 9906.1860.841929917.75860.54187
9926.44961.150759929.33560.776529940.91257.689799946.296 57.74949952.48656.20243
9963.66754.015459974.84751.404679986.02747.402619990.24145.527449997.20843.22483
10008.39 47.225210019.5755.5739610030.7562.7590910034.9665.1235810041.9368.71632
10053.1172.8052910109.0183.0407810124.4185.2750210131.3786.5742210139.2487.49509
#Mann= 3 , 0 , 0
 9816.75    0.12       0 9816.75    0.12       010139.24    0.12       0
#XS Ineff= 2 , 0
       0                               0
Bank Sta=9816.75,10139.24
Exp/Cntr=0.3,0.1

Type RM Length L Ch R = 1 ,3351.764,129.879800,129.879800,129.879800
XS GIS Cut Line= 2
1008531.94416064772955.4459218231008718.57610509773072.633421823
#Sta/Elev= 23
9910.75567.382869926.17166.049719937.97965.659469947.52766.743019949.78767.12726
9961.59564.811549973.40358.012159985.21147.022159997.01941.2690210003.94 42.5662
10008.8343.8334410020.6347.7264910032.4452.9684710041.5557.2130610044.2558.35128
10056.06 61.869610067.8763.3634810079.6764.4590310091.4865.7739210097.97 66.6256
 10115.169.4594210126.9172.0410310131.1373.06346
#Mann= 3 , 0 , 0
9910.755    0.12       09910.755    0.12       010131.13    0.12       0
#XS Ineff= 2 , 0
       0                               0
Bank Sta=9910.755,10131.13
Exp/Cntr=0.3,0.1

Type RM Length L Ch R = 1 ,3221.884,121.085000,121.085000,121.085000
XS GIS Cut Line= 3
1008437.12578458 772987.142469631008528.64721885773099.301090077
 1008711.6900875773208.767903656
#Sta/Elev= 30
9802.05272.738399812.19472.108999814.50771.637349830.32467.133629838.00765.53241
9850.91464.062039861.95863.539439889.635 64.24999893.593 63.82599902.54162.22302
9941.04460.659069946.81360.330859954.21559.524159957.916 58.34899965.86755.32527
9977.51948.428969989.17142.647689996.88340.2996210000.8239.5227210012.4747.73926
10016.3751.0396710024.1356.4810810035.7861.4914610055.3365.0915410082.3971.22964
 10094.373.7652410105.6975.9133510133.2780.51849 10152.383.0470510160.0983.63502
#Mann= 3 , 0 , 0
9802.052    0.12       09802.052    0.12       010160.09    0.12       0
#XS Ineff= 2 , 0
       0                               0
Bank Sta=9802.052,10160.09
Exp/Cntr=0.3,0.1

Type RM Length L Ch R = 1 ,3100.799,308.923700,308.923700,308.923700
XS GIS Cut Line= 4
1008406.61863983773026.6223040221008499.93461207773128.910965875
1008499.03734306773211.4597105381008599.53146702773318.234717235
#Sta/Elev= 30
 9747.0671.27422  9758.469.242089774.33365.388459804.00862.321139812.54461.78183
9818.84661.80928 9826.0862.355719833.68463.592189839.61663.762859853.15260.61611
9863.359 58.97329878.19759.696449885.518  59.6639911.60958.72182 9931.6158.80503
9941.61158.224589951.61156.546989968.07251.433249976.77249.457219986.66642.62596
9991.36339.77984 10000.439.3526810005.9541.1242810020.5450.2192310035.1457.35031
 10041.659.7380610049.7362.2322310078.9165.2938410096.5366.62607 10114.769.10757
#Mann= 3 , 0 , 0
 9747.06    0.12       0 9747.06    0.12       0 10114.7    0.12       0
#XS Ineff= 2 , 0
       0                               0
Bank Sta=9747.06,10114.7
Exp/Cntr=0.3,0.1

Type RM Length L Ch R = 1 ,2791.875,226.322700,226.322700,226.322700
XS GIS Cut Line= 4
1008288.17913663773090.3284004481008395.85141221773243.761393234
1008446.99574319773339.7691723411008544.79806024 773412.44795841
#Sta/Elev= 30
9864.75669.052769876.63168.48104 9882.6867.646269894.89765.332889907.11364.47686
 9919.3365.853879931.54762.315929946.265  59.921 9955.9857.124789963.67453.40284
9981.08344.03494 9992.6338.277769998.49136.0932310004.8534.7503110017.06  41.202
10029.2847.0130210033.3148.48333 10041.550.20963 10052.251.2526310064.9353.57736
10076.2656.5274910087.5957.7968410121.5960.2338810132.9261.6568410144.2562.57191
10170.9565.5706610186.5268.1704910220.7973.1075810258.1677.8277610282.8381.29062
#Mann= 3 , 0 , 0
9864.756    0.12       09864.756    0.12       010282.83    0.12       0
#XS Ineff= 2 , 0
       0                               0
Bank Sta=9864.756,10282.83
Exp/Cntr=0.3,0.1

Type RM Length L Ch R = 1 ,2565.552,226.322700,226.322700,226.322700
XS GIS Cut Line= 6
 1007974.3824519773237.640001617 1008152.5117256773335.943682796
1008236.56126051773361.388258814  1008261.441044773374.566942159
1008309.19842485773420.7072331881008401.52336861773543.088355934
#Sta/Elev= 30
9730.126111.27749765.23898.950479776.70595.635359788.17391.156629811.10984.53017
9822.57780.335329834.045 74.88679845.51267.217179879.91666.249659891.24964.06647
9902.53860.219989910.01358.712859947.08854.180729957.89151.194369979.20839.89541
9999.66331.56429 10009.934.5471110020.1541.87185 10031.348.4611410042.6253.90942
10054.5558.3618310067.5961.8942910080.7364.28537 10095.168.0202410134.36 79.3439
 10175.990.0947410196.9994.8433410225.7198.7108210247.0999.5311410269.7598.36639
#Mann= 3 , 0 , 0
9730.126    0.12       09730.126    0.12       010269.75    0.12       0
#XS Ineff= 2 , 0
       0                               0
Bank Sta=9730.126,10269.75
Exp/Cntr=0.3,0.1

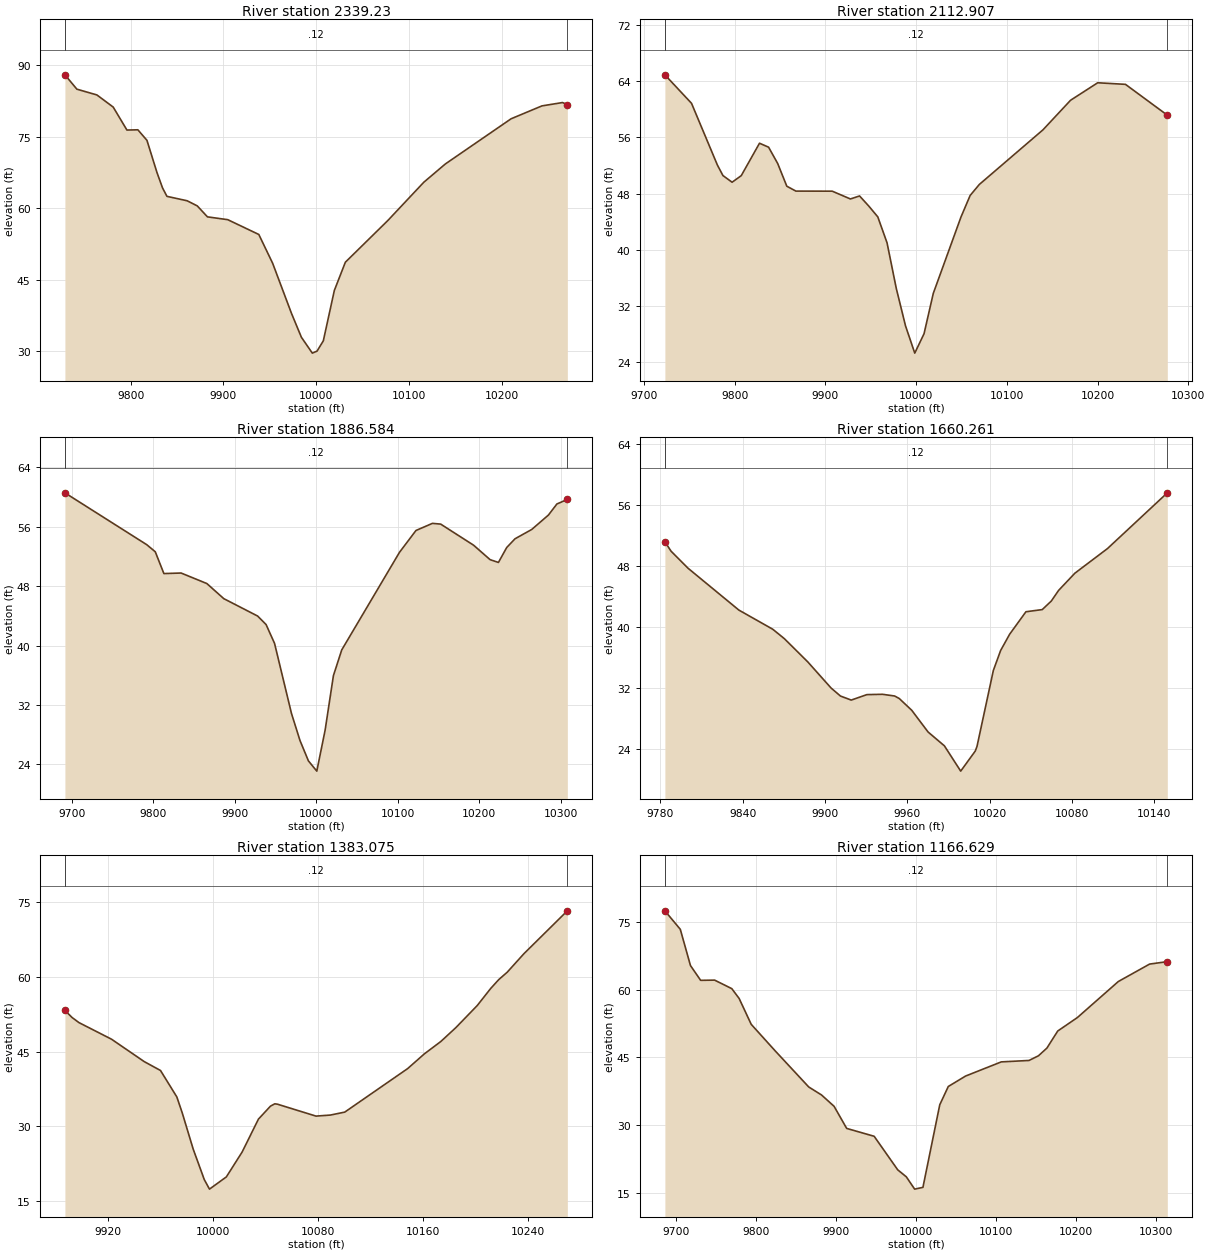
Type RM Length L Ch R = 1 , 2339.23,226.322800,226.322800,226.322800
XS GIS Cut Line= 6
1007853.02290274773435.4205512611007964.28917612773480.563199139
1008026.39298091773508.3003383751008069.35671485773530.857764984
1008160.87246007773586.3905537781008339.76340949773671.531764499
#Sta/Elev= 30
9729.08887.970879742.01484.961099763.59783.752749781.16881.209529795.97276.39322
9807.767 76.44719817.55574.238619828.34767.502019834.36664.260159839.13962.49291
9860.89461.570949871.84660.491729882.79858.196239904.70257.604999938.19654.50208
9953.10448.471399973.55637.897579984.12132.951559995.89329.62992   1000130.05462
10007.76  32.21310019.6442.7712510031.5248.6860810077.3657.4363410116.0965.44889
10139.3669.2862310210.2678.7572210243.4881.4567610265.63 82.1572 10270.981.74974
#Mann= 3 , 0 , 0
9729.088    0.12       09729.088    0.12       0 10270.9    0.12       0
#XS Ineff= 2 , 0
       0                               0
Bank Sta=9729.088,10270.9
Exp/Cntr=0.3,0.1

Type RM Length L Ch R = 1 ,2112.907,226.322700,226.322700,226.322700
XS GIS Cut Line= 6
 1007802.2272814773759.1499596381007894.38975584773775.623718807
1007971.85476048773778.9473718621008148.03305015 773751.70951452
1008216.02400191773748.9557051461008349.70217794773772.414275217
#Sta/Elev= 30
9723.077 64.91429752.44560.857359780.98152.069879787.06850.577779797.16549.62625
9807.26250.564829827.38255.17792 9837.4154.613099847.43752.291649857.46549.06349
9867.47448.364249907.53248.354649927.62147.244349937.66547.674479947.70946.25597
  9957.844.691799967.98441.001669978.16834.512329988.35129.184739998.53525.30322
10008.7528.0610810018.9633.8075110049.4944.67466 10059.647.7472810069.7249.31154
10139.8657.0824110170.2661.2904310200.2163.7843210230.8263.5579910276.9659.17254
#Mann= 3 , 0 , 0
9723.077    0.12       09723.077    0.12       010276.96    0.12       0
#XS Ineff= 2 , 0
       09937.987                       0
Bank Sta=9723.077,10276.96
Exp/Cntr=0.3,0.1

Type RM Length L Ch R = 1 ,1886.584,226.322700,226.322700,226.322700
XS GIS Cut Line= 6
 1007790.9159919773893.3575740051007948.47570151773949.969566816
1008077.89656136 773986.266633791008137.63720779773998.663705914
1008286.09608474  774019.52081281008387.44700487774042.055737457
#Sta/Elev= 30
9691.67260.547219791.99953.578439802.57252.617929813.14449.683949834.289 49.7559
9865.88548.341929886.65746.31075  9928.243.969859938.58642.822449948.97240.29104
9969.74430.86504 9980.13 27.24189990.51524.4864510000.8323.1042410011.0328.61236
10021.2435.9623810031.4439.4133610102.3752.5529610122.5755.4828310142.7656.43953
10152.8656.3388110193.2553.5025310213.5451.5543410223.7451.1800410233.9353.19204
10244.1354.3659210264.5955.6146810285.1657.5613810295.4859.0448810308.3259.65632
#Mann= 3 , 0 , 0
9691.672    0.12       09691.672    0.12       010308.32    0.12       0
#XS Ineff= 2 , 0
       0                               0
Bank Sta=9691.672,10308.32
Exp/Cntr=0.3,0.1

Type RM Length L Ch R = 1 ,1660.261,277.186200,277.186200,277.186200
XS GIS Cut Line= 4
1007891.31916067774073.9355051371007997.43895233774150.758421823
1008015.66811898774183.9615468231008181.68374401774290.732380152
#Sta/Elev= 30
9783.25651.17176  9787.849.924679800.14647.694719837.18242.205719861.872 39.6919
9870.33838.456729887.39135.410129904.44431.968949911.25330.922149919.10330.39305
9930.51131.110289941.91931.151199950.75430.926969954.06230.607159963.23829.04818
9975.12726.202549987.01724.387849998.90721.0688210009.5223.70383 10010.824.31956
10022.6934.2709610028.0136.8990810034.5839.0344910046.4641.9871410058.3542.26723
10064.9843.3969510070.2444.7795910082.1347.0435110105.9150.2771110149.5357.59309
#Mann= 3 , 0 , 0
9783.256    0.12       09783.256    0.12       010149.53    0.12       0
#XS Ineff= 2 , 0
       0                               0
Bank Sta=9783.256,10149.53
Exp/Cntr=0.3,0.1

Type RM Length L Ch R = 1 ,1383.075,216.445800,216.445800,216.445800
XS GIS Cut Line= 4
1007816.44936898774161.8261301371007946.65770233774258.180296808
1007978.55874401774329.7948801521008091.18895233774417.034463495
#Sta/Elev= 30
9886.93253.293719892.268 51.88949897.56950.84799 9922.4547.50279 9947.3343.00943
9959.77141.217749972.21135.907549976.32432.712029984.65125.447779993.13519.29716
9997.09117.3816810009.9519.8385810021.9724.8325610034.4131.4524310043.5734.05166
10046.8534.5216210048.9134.4440610078.2732.0514810089.2232.2623310100.1732.85416
10148.1141.5991510160.7644.5394610173.4147.04901 10184.849.8196310201.1354.26648
10211.3557.6865410217.4659.46375   1022460.9714310236.6564.6692110269.78 73.2951
#Mann= 3 , 0 , 0
9886.932    0.12       09886.932    0.12       010269.78    0.12       0
#XS Ineff= 2 , 0
       0                               0
Bank Sta=9886.932,10269.78
Exp/Cntr=0.3,0.1

Type RM Length L Ch R = 1 ,1166.629,216.445900,216.445900,216.445900
XS GIS Cut Line= 6
1007639.87114813774196.6787505931007741.30616692774281.111286231
1007809.28366412774356.4990086771007837.87120115774401.975592597
1007894.46987262774540.944022414 1008007.8673741774692.015253897
#Sta/Elev= 30
9686.42777.418859705.65373.327939718.36165.304089731.06962.033529748.52762.08013
9769.94660.19605  9779.158.026589794.175    52.39823.91646.457519865.97938.43324
9881.93736.665379897.639 34.14879913.34229.26064 9947.6427.520749977.08420.09028
9987.76918.54874 9998.1915.8232710008.5316.2139510029.5234.4818510040.1738.53812
10061.8140.8527310106.3343.9844610140.9744.3015910152.7545.3382910163.2647.03566
10176.8150.8184910201.3653.8026510252.4761.7772410291.4765.6307410313.5966.17272
#Mann= 3 , 0 , 0
9686.427    0.12       09686.427    0.12       010313.59    0.12       0
#XS Ineff= 2 , 0
       0                               0
Bank Sta=9686.427,10313.59
Exp/Cntr=0.3,0.1