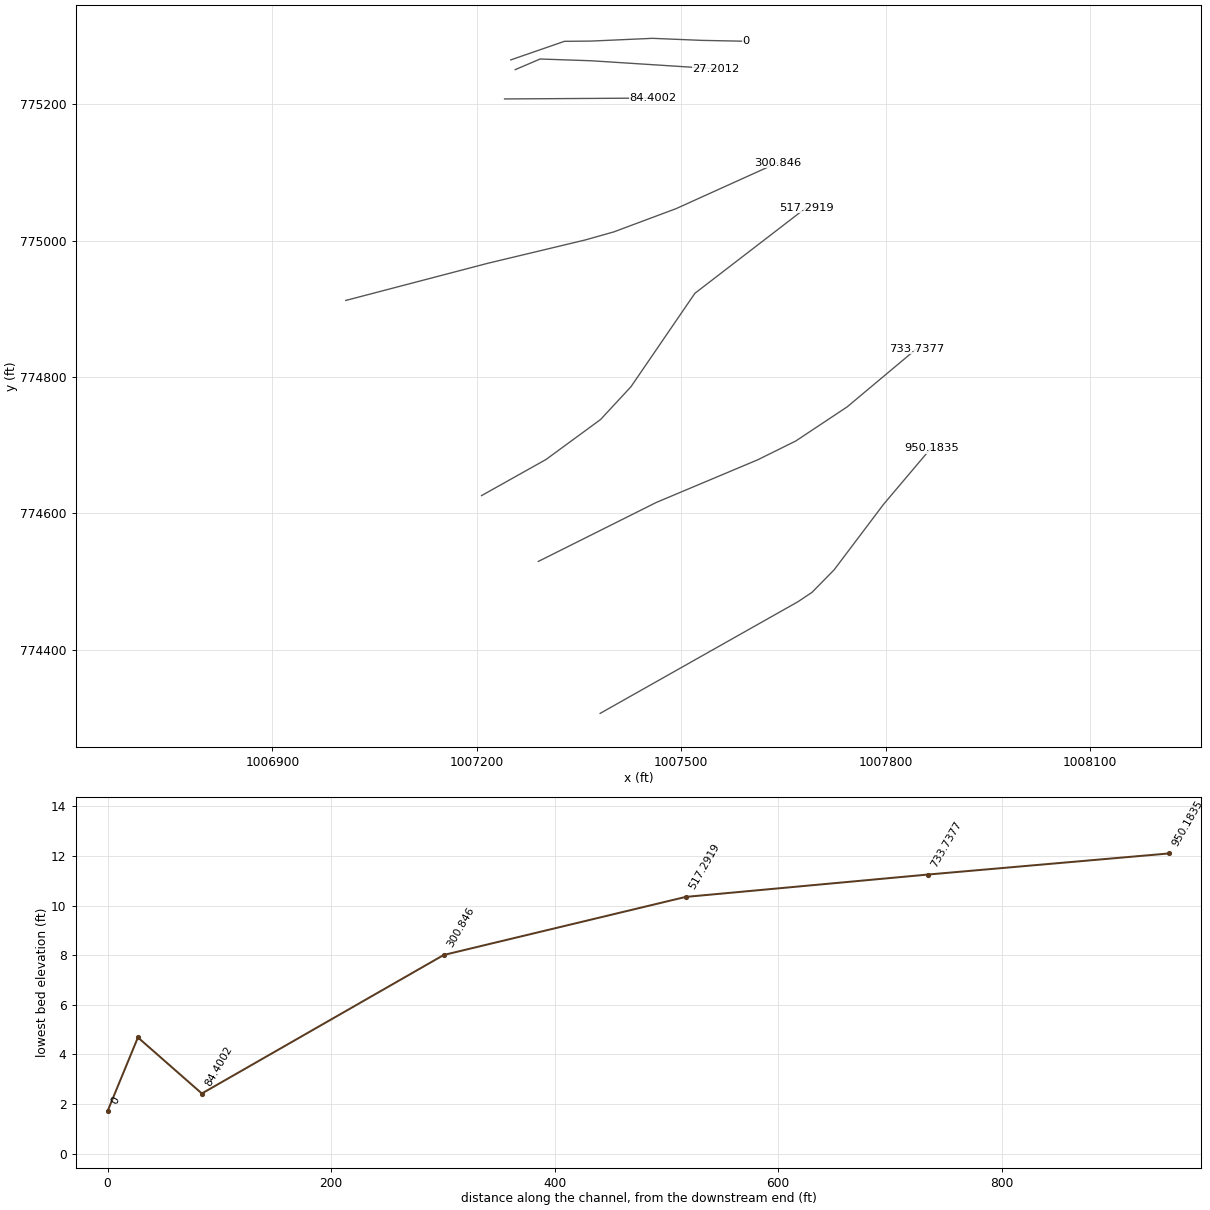
HEC-RAS study 199_ras.prj: 199

--- 199_ras.g01 (geometry) --- (continued)

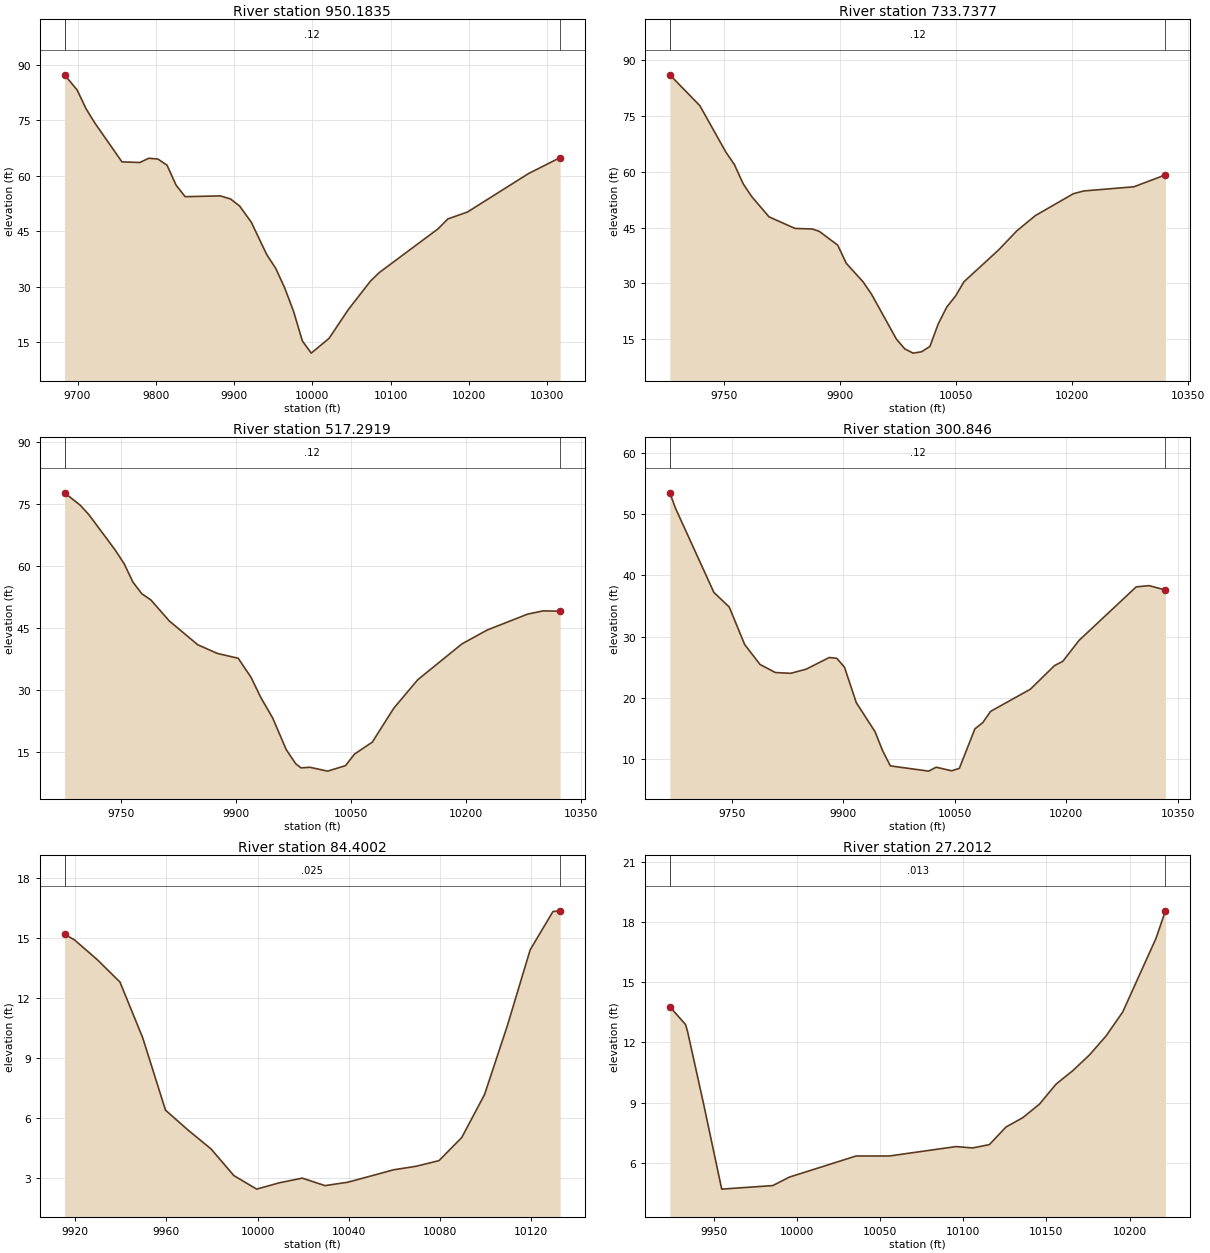
Type RM Length L Ch R = 1 ,950.1835,216.445800,216.445800,216.445800
XS GIS Cut Line= 6
1007380.95705781774306.3781647351007671.05340285 774470.13084403
  1007691.746467774483.9434484891007724.16195855774516.926333905
1007796.74902139774613.1050515811007866.57715382774695.732381235
#Sta/Elev= 30
 9683.4487.247549699.51483.15037 9710.9678.068759721.71874.359649756.74363.74588
9779.63463.581349791.14264.730059802.73464.510119814.32662.843569825.91857.45157
 9837.5154.347169882.35154.561959895.46953.730389907.06151.826149921.89547.48423
9941.66738.728699953.30434.942749964.619 29.72899975.93423.406619987.24915.38405
9998.56412.1063310021.3716.1087510045.8423.8493110074.0731.5141110085.2433.82344
10160.5845.6761610173.1148.3378310198.1650.2119610276.2660.60785 10316.564.89505
#Mann= 3 , 0 , 0
 9683.44    0.12       0 9683.44    0.12       0 10316.5    0.12       0
#XS Ineff= 2 , 0
       0                               0
Bank Sta=9683.44,10316.5
Exp/Cntr=0.3,0.1

Type RM Length L Ch R = 1 ,733.7377,216.445800,216.445800,216.445800
XS GIS Cut Line= 6
1007290.24548602774529.3207120131007463.12623905774615.761176772
1007612.21278145774678.4468031251007667.82904327774705.942463529
1007743.30691805774756.0301006021007845.51765599774841.611305783
#Sta/Elev= 30
9679.45886.090989718.31577.786989751.85665.338379763.03661.931319774.21756.82947
9785.397 53.34739807.75847.900929841.29944.789139863.65944.638219872.74543.99968
9896.67240.27503 9907.6135.428429929.45530.412049940.238 27.12839972.58515.00307
9983.36812.386449994.15111.2526810004.9611.6105710015.8113.0312510026.6619.12378
 10037.623.6148810049.2826.6865310059.9130.4441410104.9439.04928 10128.444.15913
10152.3848.2546810201.4754.1248810215.03  54.86510279.8255.98598 10320.559.18995
#Mann= 3 , 0 , 0
9679.458    0.12       09679.458    0.12       0 10320.5    0.12       0
#XS Ineff= 2 , 0
       0                               0
Bank Sta=9679.458,10320.5
Exp/Cntr=0.3,0.1

Type RM Length L Ch R = 1 ,517.2919,216.445900,216.445900,216.445900
XS GIS Cut Line= 6
1007206.93837832 774625.882200311007301.44409412774678.821702239
1007381.51506501774737.4881982661007426.09120551774785.548869401
1007519.94044139774922.6871060461007683.48157527775048.461763385
#Sta/Elev= 30
9676.64277.627599697.06874.637299708.37672.35489 9742.78 63.78589754.36260.49407
9765.94456.019929777.41553.240679789.27251.728369813.35446.646189850.41740.90591
9876.00338.806389903.23237.632169920.08232.997789932.58428.204759948.26423.17972
9965.92415.550049978.20612.154729985.17411.136929996.722 11.285710019.9810.35183
 10043.311.6817310054.9814.4717610078.1817.3572410106.2925.5690710137.5432.44484
10195.1841.1052110228.1844.4665210280.9748.3089910301.1849.0888510323.3649.02059
#Mann= 3 , 0 , 0
9676.642    0.12       09676.642    0.12       010323.36    0.12       0
#XS Ineff= 2 , 0
       0                               0
Bank Sta=9676.642,10323.36
Exp/Cntr=0.3,0.1

Type RM Length L Ch R = 1 , 300.846,216.445800,216.445800,216.445800
XS GIS Cut Line= 6
1007007.69049808774912.1871954071007216.02587949774966.703556611
1007358.59402622775000.8222216581007401.04688172775012.792429115
1007492.34773505775046.8892176741007640.83352355775114.053543603
#Sta/Elev= 30
9666.73553.48624 9674.2950.982389725.97437.215259746.64734.823429767.32128.71358
9787.99425.441319808.66724.124089829.34123.995779850.01424.666429881.024 26.5731
9891.31626.447749901.602 24.99749917.49719.199879942.747 14.44769953.03311.31209
 9963.328.86984210014.728.01128310024.998.65255910045.738.06418310056.118.466865
10076.9714.9145510087.5515.9306410098.1217.7763810151.6121.3965810184.1625.26355
10195.1425.9416310217.0929.3720810293.9138.1170710311.2838.3191610333.2437.60818
#Mann= 3 , 0 , 0
9666.735    0.12       09666.735    0.12       010333.24    0.12       0
#XS Ineff= 2 , 0
       0                               0
Bank Sta=9666.735,10333.24
Exp/Cntr=0.3,0.1

Type RM Length L Ch R = 1 , 84.4002,57.199000,57.199000,57.199000
XS GIS Cut Line= 2
1007240.71152177  775207.8330746 1007458.1594384775209.135157943
#Sta/Elev= 24
9915.29315.191959919.58114.923829929.58113.932119939.58212.807389949.58210.01113
9959.5826.3829299969.5825.3754489979.5824.4373999989.5823.1032629999.5832.425298
10009.582.74390910019.582.97628510029.582.60091110039.582.77185710049.583.079909
10059.583.39239710069.583.57167510079.583.85342710089.585.01400410099.587.167344
10109.5810.6189110119.5814.4163510129.58 16.338110132.7416.37333
#Mann= 3 , 0 , 0
9915.293   0.025       09915.293   0.025       010132.74   0.025       0
#XS Ineff= 2 , 0
       0                               0
Bank Sta=9915.293,10132.74
Exp/Cntr=0.3,0.1

Type RM Length L Ch R = 1 , 27.2012,27.201200,27.201200,27.201200
XS GIS Cut Line= 4
1007256.33652177775250.8018245851007292.79485512775266.426824585
1007368.31568843775263.8226579431007550.60735509775252.103907928
#Sta/Elev= 22
 9923.6313.781899933.05612.895449934.28712.546959943.9358.9295719954.8154.685749
9985.5144.862892 9995.52 5.2861910035.546.33755610055.586.33876710095.666.808253
10105.686.739861 10115.7 6.9058610125.727.78550410135.758.24710410145.778.922147
10155.799.92232110165.8110.5922710175.8311.3741910185.8512.3246110195.8713.52048
10215.9117.2010210221.5318.56636
#Mann= 3 , 0 , 0
 9923.63   0.013       0 9923.63   0.013       010221.53   0.013       0
#XS Ineff= 2 , 0
       0                               0
Bank Sta=9923.63,10221.53
Exp/Cntr=0.3,0.1

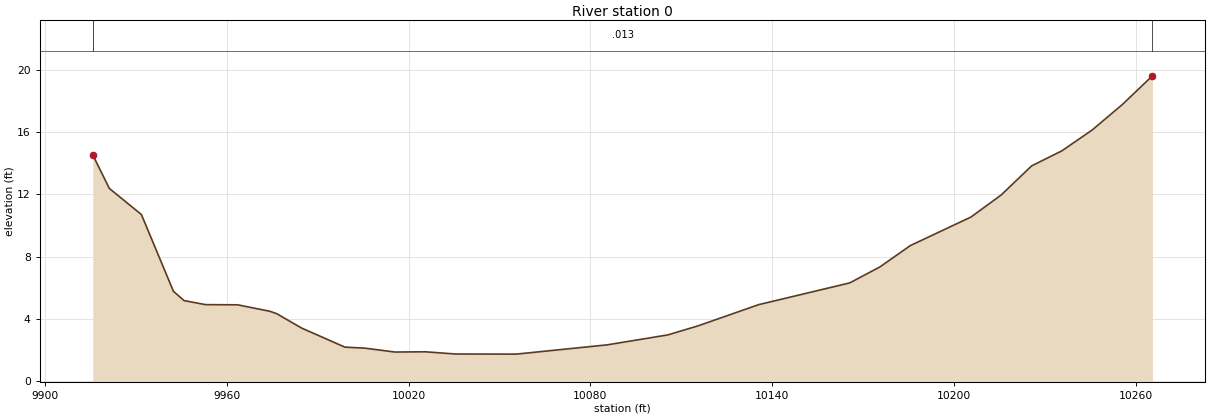
Type RM Length L Ch R = 1 ,       0,0.000000,0.000000,0.000000
XS GIS Cut Line= 6
1007249.82610509775265.1247412711007328.47764376775292.363114268
1007367.31780171775292.7142530831007457.55967635 775296.75222145
1007529.77402174  775293.77057461007594.87818843775292.468491256
#Sta/Elev= 30
9915.76514.544819921.24112.385819931.82410.703319942.4065.7555779945.9425.157513
9952.989 4.899389963.5724.8876039974.1544.475656  9976.54.3155299984.7373.387839
    99992.16102610005.522.09685310015.521.84503210025.521.86116410035.521.718177
10055.541.71077710085.572.30760910105.592.948219 10115.63.53387210135.624.900501
10165.656.29942810175.657.33503310185.668.70537610205.6810.5450310215.6811.97035
10225.6813.8375410235.6814.8086710245.6816.1520710255.6917.8023710265.5719.64223
#Mann= 3 , 0 , 0
9915.765   0.013       09915.765   0.013       010265.57   0.013       0
#XS Ineff= 2 , 0
       0                               0
Bank Sta=9915.765,10265.57
Exp/Cntr=0.3,0.1